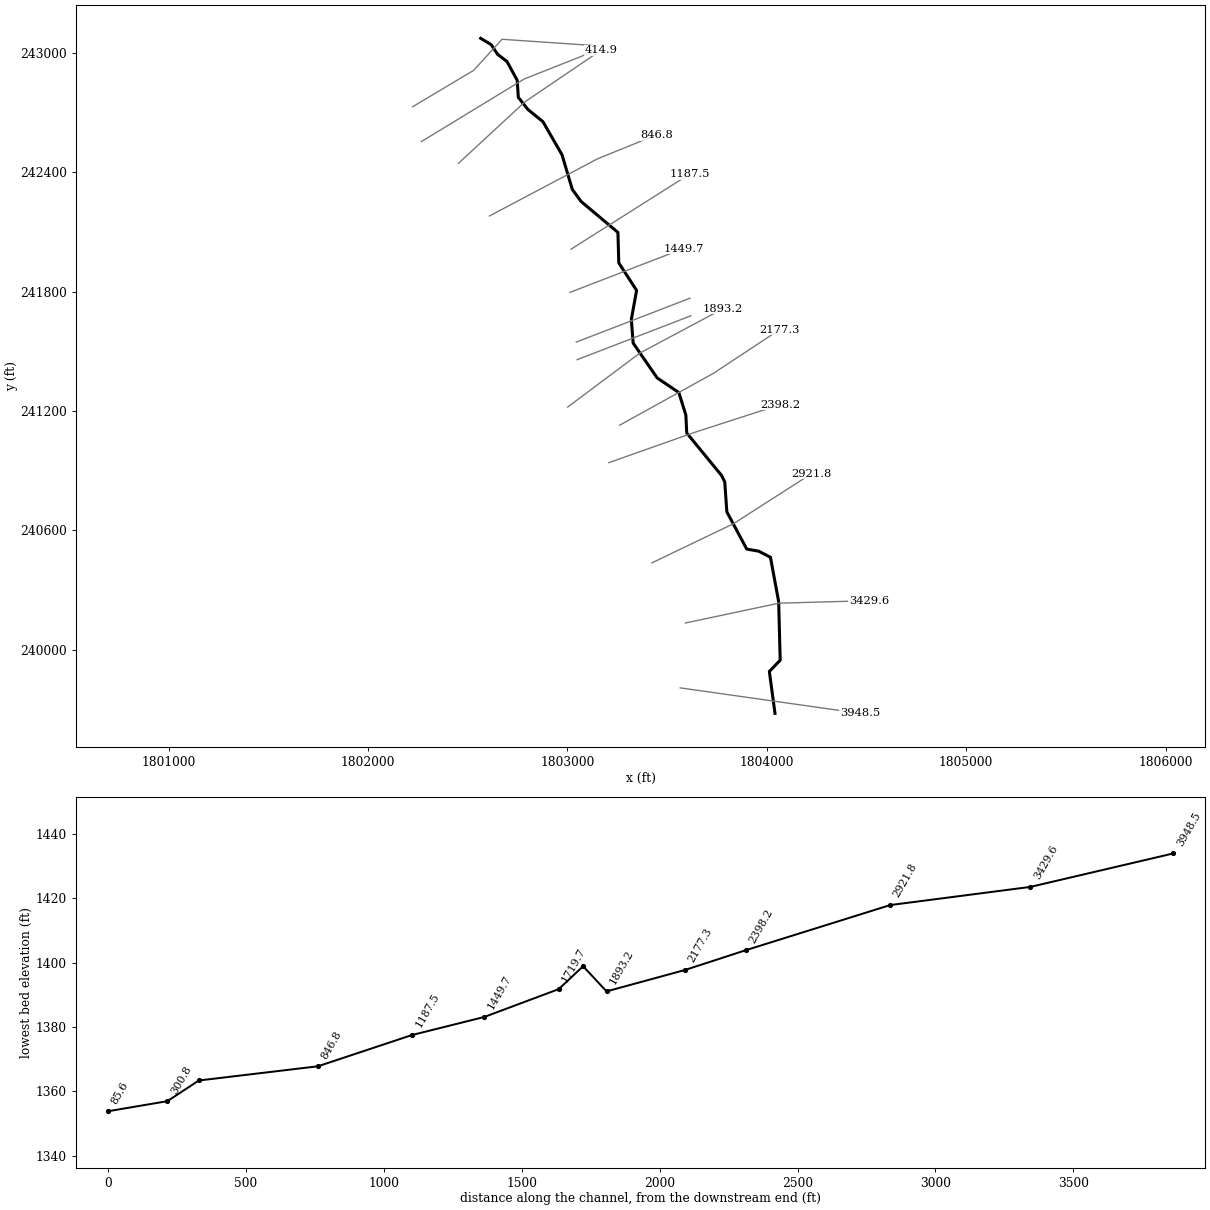
--- ElkinsBr.prj (project) ---

Proj Title=ElkinsBr
Current Plan=p01
Default Exp/Contr=0,0
English Units
Geom File=g01
Flow File=f01
Plan File=p01
BEGIN DESCRIPTION:
END DESCRIPTION:
DSS Export Rating Curves= 0
DSS Export Rating Curve Sorted= 0
DSS Export Volume Flow Curves= 0
DXF OffsetX= 0
DXF OffsetY= 0
DXF ScaleX= 0
DXF ScaleY= 0

--- ElkinsBr.p01 (plan) ---

Plan Title=Floodplain
Program Version=4.00
Geom File=g01
Flow File=f01
K Sum by GR=0
Std Step Tol=0.01
Critical Tol=0.01
Num of Std Step Trials=20
Max Error Tol=0.3
Flow Tol Ratio=0.001
Split Flow NTrial=30
Split Flow Tol=0.02
Split Flow Ratio=0.02
Log Output Level=0
Friction Slope Method=1
Unsteady Friction Slope Method=2
Unsteady Bridges Friction Slope Method=1
Global Log Level=0
CheckData=False
Run HTab=0
Run UNet=0
Run PostProcess=0
UNET Theta=0
UNET Theta Warmup=0
UNET ZTol=0
UNET ZSATol=0
UNET MxIter=0
UNET MaxInSteps=0
UNET DtIC=0
UNET DtMin=0
UNET MaxCRTS=0
UNET WFStab=0
UNET SFStab=0
UNET WFX=0
UNET SFX=0
UNET DSS MLevel=0
UNET DZMax Abort=0
UNET Convert EG Bridges=0
UNET Use Existing IB Tables=0
UNET Froude Limit=0
UNET Froude Power=0
Write IC File=0
Echo Input=False
Echo Output=False
Write Detailed=0

--- ElkinsBr.f01 (steady flow) ---

Flow Title=NFF Regression Equation
Program Version=4.00
Number of Profiles=1
Profile Names=P100yr
River Rch & RM=ElkinsBr,Main      ,3948.5
554.9799
River Rch & RM=ElkinsBr,Main      ,2921.8
572.5584
River Rch & RM=ElkinsBr,Main      ,2921.8
682.8635
River Rch & RM=ElkinsBr,Main      ,1893.2
741.7643
River Rch & RM=ElkinsBr,Main      ,85.6
779.3466
Boundary for River Rch & Prof#=ElkinsBr,Main      ,1
Up Type=0
Dn Type=3
Dn Slope=0.027737

--- ElkinsBr.g01 (geometry) ---

Geom Title=USGS 10m DEM
Program Version=4.00

River Reach=ElkinsBr     ,Main
Reach XY= 30
     1804041.031      239680.997     1804012.796      239891.674
     1804067.094      239948.144     1804059.480      240242.240
     1804018.362      240465.325     1803959.748      240495.944
     1803899.342      240506.625     1803799.652      240693.659
     1803789.154      240844.132     1803772.531      240877.376
     1803598.438      241089.962     1803594.064      241180.071
     1803558.910      241293.147     1803449.880      241366.988
     1803329.890      241541.780     1803320.706      241660.860
     1803347.078      241806.426     1803257.745      241944.617
     1803253.391      242097.898     1803068.965      242253.177
     1803024.550      242314.247     1802973.196      242487.742
     1802877.426      242654.298     1802802.476      242715.368
     1802753.897      242776.439     1802748.346      242862.492
     1802696.991      242956.874     1802649.800      242992.961
     1802617.877      243041.540     1802565.152      243073.207

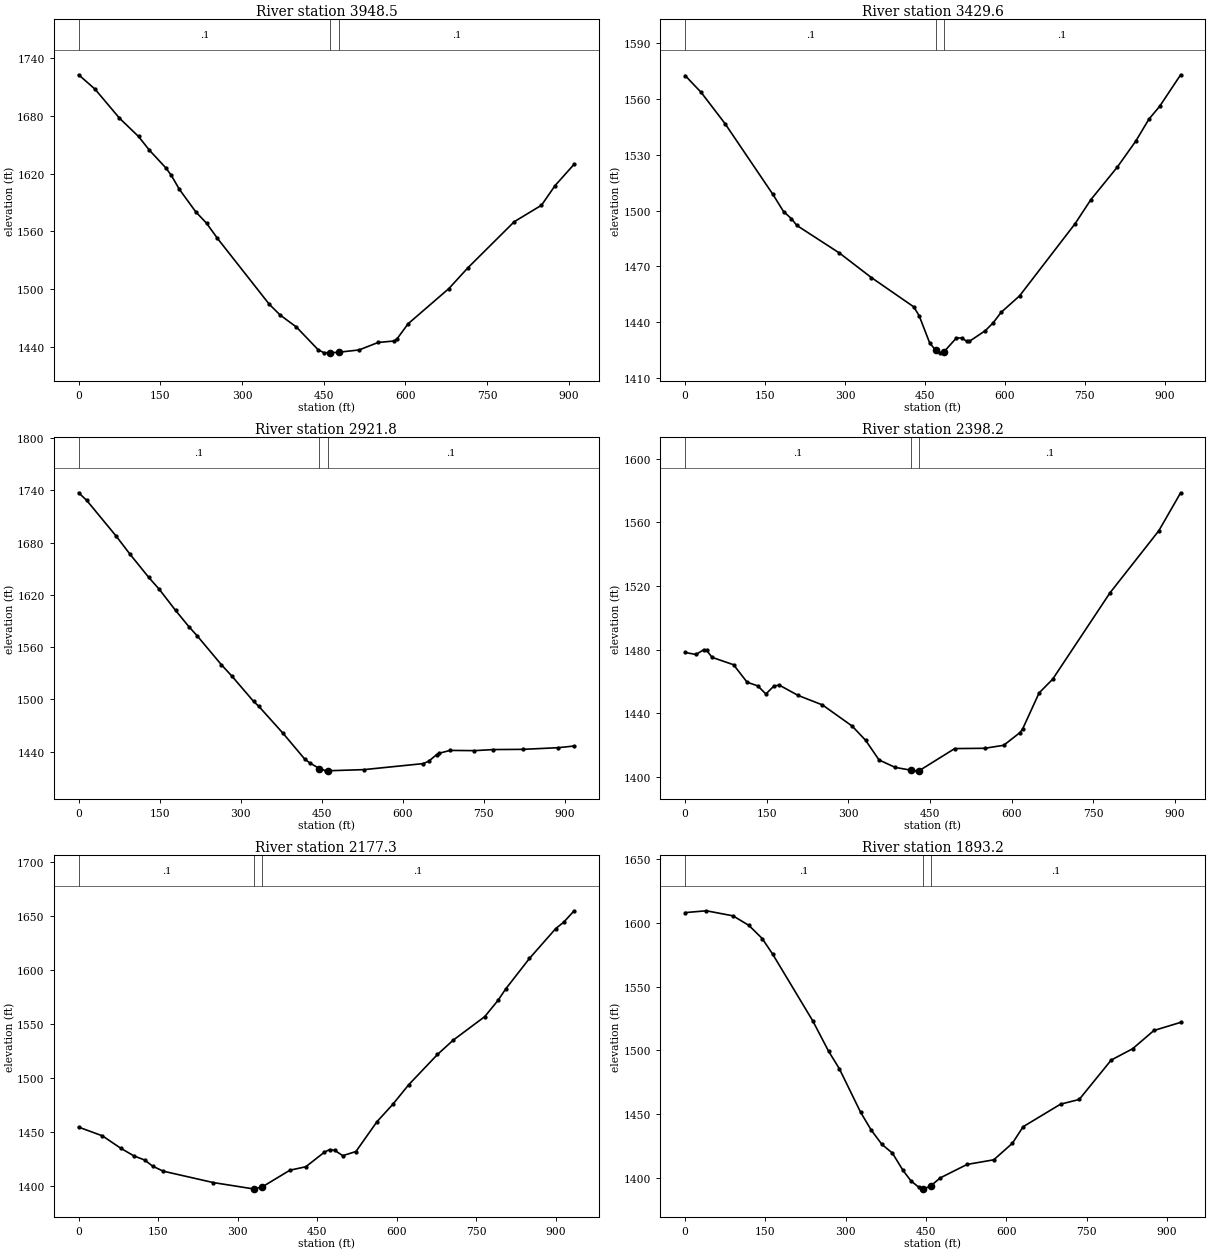
Type RM Length L Ch R = 1 ,3948.5,522,518.9,523
XS GIS Cut Line= 3
     1803565.609      239809.171     1804016.100      239745.274
     1804466.591      239681.377
#Sta/Elev= 30
       0 1722.67    30.0 1707.81    75.0 1677.62   110.0 1658.61   130.0 1644.36
   160.0 1626.08   170.0 1618.42   185.0 1603.77   215.0 1580.46   235.0 1568.53
   255.0 1552.78   350.0 1484.51   370.0 1473.28   400.0 1460.75   440.0 1437.13
   450.0 1434.26   460.0 1434.01   462.5 1434.03   477.5 1434.62   515.0 1437.02
   550.0 1444.77   580.0 1446.34   585.0 1448.72   605.0 1464.16   680.0 1500.79
   715.0 1522.38   800.0 1570.14   850.0 1587.25   875.0 1607.70   910.0 1629.84
#Mann= 3 , 0 , 0
       0     0.1       0   462.5   0.045       0   477.5     0.1       0
Bank Sta=   462.5,   477.5
Exp/Cntr=0.3,0.1

Type RM Length L Ch R = 1 ,3429.6,502.7,507.9,519.7
XS GIS Cut Line= 3
     1803591.924      240135.218     1804060.609      240234.780
     1804511.175      240247.296
#Sta/Elev= 30
       0 1572.49    30.0 1563.48    74.9 1546.68   164.7 1508.70   184.7 1499.46
   199.6 1495.62   209.6 1492.01   289.5 1477.20   349.4 1464.04   429.2 1448.26
   439.2 1443.52   459.2 1428.74   470.1 1425.13   479.1 1423.59   485.1 1423.93
   508.9 1431.52   518.8 1431.59   528.7 1429.76   533.6 1429.78   563.4 1435.50
   578.2 1439.74   593.1 1445.36   627.7 1454.20   731.8 1492.92   761.5 1505.87
   811.0 1523.30   845.7 1537.26   870.4 1549.08   890.3 1555.86   929.9 1572.89
#Mann= 3 , 0 , 0
       0     0.1       0   470.1   0.045       0   485.1     0.1       0
Bank Sta=   470.1,   485.1
Exp/Cntr=0.3,0.1

Type RM Length L Ch R = 1 ,2921.8,527,523.6,517.5
XS GIS Cut Line= 3
     1803423.985      240437.340     1803832.525      240633.964
     1804223.057      240884.718
#Sta/Elev= 30
       0 1737.30    15.0 1728.54    69.8 1687.28    94.7 1667.09   129.5 1640.36
   149.5 1626.29   179.4 1602.27   204.3 1583.41   219.2 1573.24   264.1 1539.97
   284.0 1526.57   323.8 1497.80   333.8 1491.91   378.7 1460.90   418.5 1431.53
   428.5 1426.81   445.9 1420.56   458.4 1417.95   460.9 1418.02   528.2 1419.34
   638.0 1426.25   648.0 1428.93   663.0 1436.62   668.0 1438.23   687.9 1441.43
   732.8 1441.14   767.8 1442.38   822.7 1442.63   887.6 1444.53   917.5 1446.47
#Mann= 3 , 0 , 0
       0     0.1       0   445.9   0.045       0   460.9     0.1       0
Bank Sta=   445.9,   460.9
Exp/Cntr=0.3,0.1

Type RM Length L Ch R = 1 ,2398.2,218,220.9,224.8
XS GIS Cut Line= 3
     1803207.720      240940.895     1803636.850      241092.746
     1804069.654      241233.006
#Sta/Elev= 30
       0 1478.27    19.8 1476.98    34.6 1480.02    39.6 1479.54    49.5 1475.20
    89.1 1470.53   113.8 1459.60   133.6 1457.24   148.4 1452.16   163.3 1457.23
   173.2 1457.71   207.8 1451.24   252.3 1445.31   306.8 1432.04   331.5 1423.12
   356.2 1410.76   385.9 1406.07   415.1 1404.31   425.5 1403.91   430.1 1404.03
   495.2 1417.89   550.2 1418.07   585.2 1419.95   615.2 1427.96   620.2 1430.39
   650.2 1452.83   675.2 1461.50   780.2 1515.60   870.2 1554.75   910.2 1578.55
#Mann= 3 , 0 , 0
       0     0.1       0   415.1   0.045       0   430.1     0.1       0
Bank Sta=   415.1,   430.1
Exp/Cntr=0.3,0.1

Type RM Length L Ch R = 1 ,2177.3,278.7,284.1,285
XS GIS Cut Line= 3
     1803262.342      241129.206     1803732.829      241390.070
     1804063.567      241609.009
#Sta/Elev= 30
       0 1454.82    44.8 1446.76    79.7 1435.19   104.6 1428.12   124.5 1424.42
   139.5 1418.75   159.4 1414.10   254.0 1403.55   328.8 1397.75     331 1397.78
     346 1399.45   398.5 1414.98   428.4 1418.15   463.2 1431.50   473.2 1434.09
   483.2 1433.30   498.1 1428.42   523.0 1432.24   562.8 1459.91   592.5 1475.85
   622.2 1493.82   676.8 1521.99   706.5 1535.23   766.0 1556.99   790.8 1571.91
   805.7 1582.71   850.3 1610.79   899.9 1638.41   914.8 1644.24   934.6 1654.83
#Mann= 3 , 0 , 0
       0     0.1       0     331   0.045       0     346     0.1       0
Bank Sta=     331,     346
Exp/Cntr=0.3,0.1

Type RM Length L Ch R = 1 ,1893.2,91.2,85,82.3
XS GIS Cut Line= 3
     1803001.572      241220.316     1803362.951      241491.354
     1803780.506      241714.737
#Sta/Elev= 30
       0 1608.23    39.7 1609.67    89.4 1605.69   119.1 1598.19   144.0 1587.86
   163.8 1575.37   238.3 1523.19   268.1 1499.14   287.9 1485.61   327.6 1451.39
   347.5 1437.31   367.3 1426.14   387.2 1419.14   407.0 1405.53   421.9 1397.29
   436.8 1392.22   444.2 1391.18   446.8 1391.10   459.2 1393.60   476.6 1399.74
   526.5 1410.28   576.4 1413.92   611.2 1426.96   631.2 1439.93   701.0 1457.64
   735.9 1461.36   795.7 1492.35   835.6 1501.20   875.4 1515.57   925.3 1521.95
#Mann= 3 , 0 , 0
       0     0.1       0   444.2   0.045       0   459.2     0.1       0
Bank Sta=   444.2,   459.2
Exp/Cntr=0.3,0.1

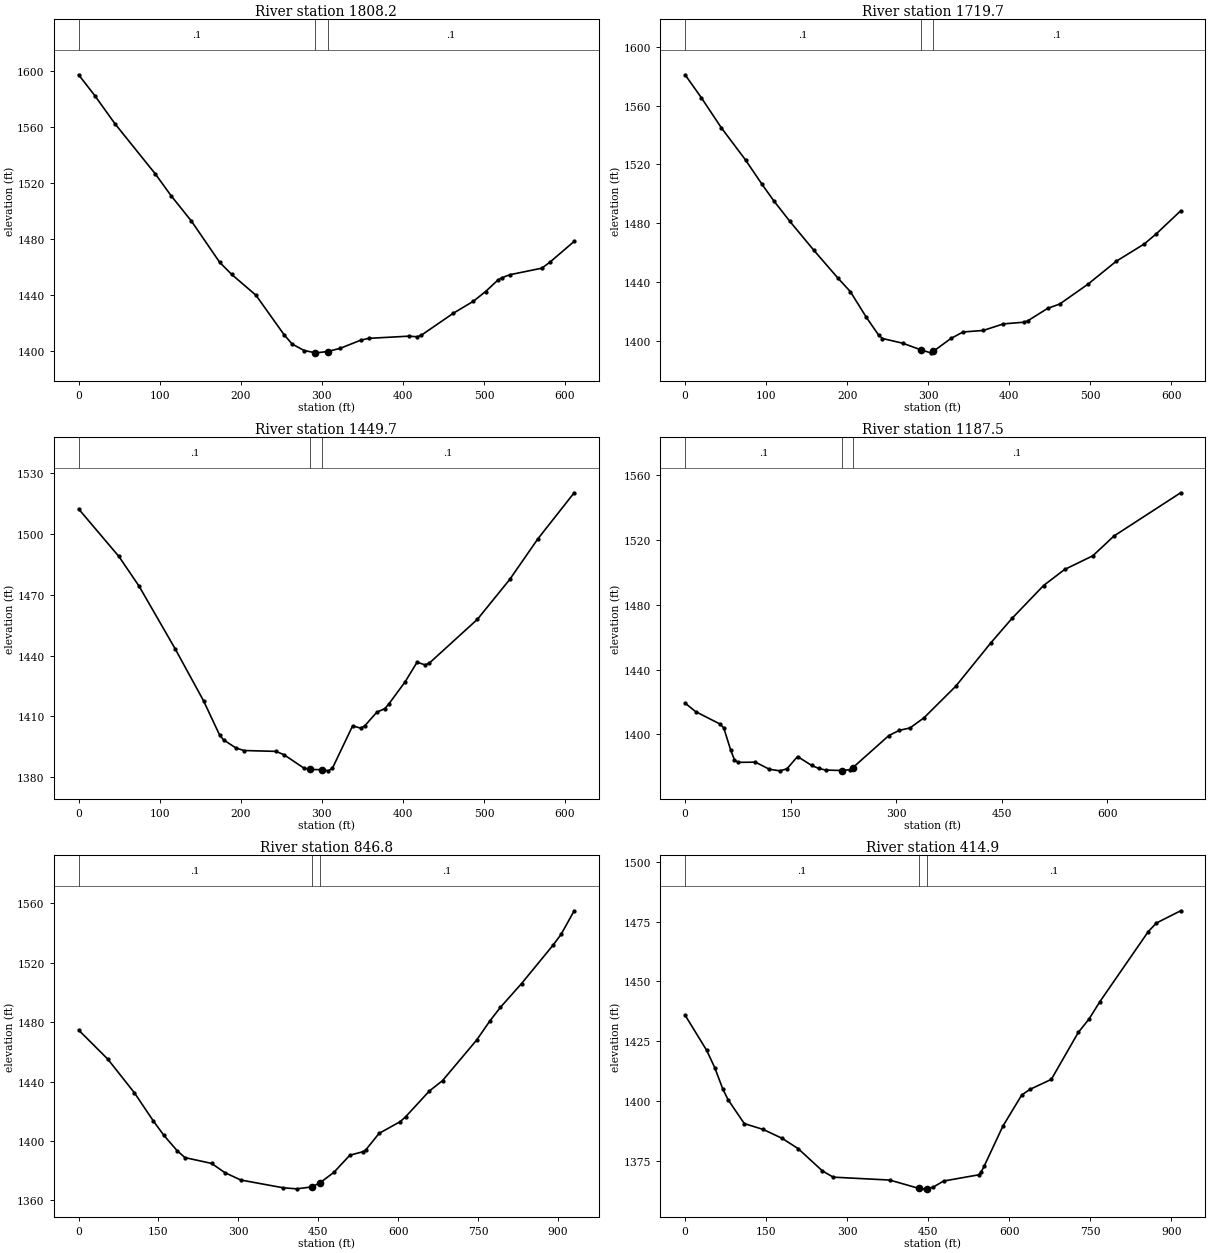
Type RM Length L Ch R = 1 ,1808.2,88.5,88.5,88.5
XS GIS Cut Line= 2
     1803048.752      241458.314     1803618.889      241678.821
#Sta/Elev= 30
       0 1597.39    19.9 1582.56    44.7 1562.53    94.4 1526.77   114.3 1510.90
   139.2 1492.91   174.0 1463.54   188.8 1454.88   218.7 1440.08   253.5 1411.81
   263.4 1405.19   278.3 1400.56   292.1 1398.96   293.2 1398.92   307.1 1399.86
   323.0 1402.20   347.9 1407.94   357.8 1409.26   407.5 1410.83   417.5 1410.40
   422.4 1411.35   462.2 1427.17   487.0 1435.76   502.0 1442.67   516.9 1450.69
   521.8 1452.46   531.8 1454.65   571.5 1459.37   581.5 1463.69   611.3 1478.47
#Mann= 3 , 0 , 0
       0     0.1       0   292.1   0.045       0   307.1     0.1       0
Bank Sta=   292.1,   307.1
Exp/Cntr=0.3,0.1

Type RM Length L Ch R = 1 ,1719.7,270.7,270,269.3
XS GIS Cut Line= 2
     1803044.644      241546.831     1803614.781      241767.339
#Sta/Elev= 30
       0 1581.05    19.9 1565.57    44.7 1544.98    74.6 1523.04    94.4 1506.89
   109.3 1495.34   129.2 1481.32   159.0 1461.50   188.8 1442.50   203.8 1433.51
   223.6 1415.98   238.6 1403.99   243.5 1401.55   268.4 1398.36   291.4 1393.71
   303.2 1391.80   306.4 1392.88   328.0 1401.62   342.9 1406.00   367.8 1407.03
   392.6 1411.50   417.5 1412.62   422.4 1413.49   447.3 1422.07   462.2 1425.04
   497.0 1438.53   531.8 1454.11   566.6 1465.96   581.5 1472.93   611.3 1488.44
#Mann= 3 , 0 , 0
       0     0.1       0   291.4   0.045       0   306.4     0.1       0
Bank Sta=   291.4,   306.4
Exp/Cntr=0.3,0.1

Type RM Length L Ch R = 1 ,1449.7,258.7,262.2,266.1
XS GIS Cut Line= 2
     1803013.025      241796.577     1803583.162      242017.085
#Sta/Elev= 30
       0 1512.36    49.7 1488.91    74.6 1474.25   119.3 1443.19   154.1 1417.69
   174.0 1400.73   178.9 1398.40   193.8 1394.49   203.8 1393.17   243.5 1392.74
   253.5 1391.05   278.3 1384.38   285.7 1383.82   300.7 1383.69   308.1 1383.14
   313.1 1384.46   338.0 1405.33   347.9 1404.22   352.9 1405.32   367.8 1412.06
   377.7 1413.85   382.7 1416.16   402.6 1426.96   417.5 1436.75   427.4 1435.43
   432.4 1436.22   492.0 1457.94   531.8 1477.58   566.6 1497.67   611.3 1520.35
#Mann= 3 , 0 , 0
       0     0.1       0   285.7   0.045       0   300.7     0.1       0
Bank Sta=   285.7,   300.7
Exp/Cntr=0.3,0.1

Type RM Length L Ch R = 1 ,1187.5,341.5,340.7,339.5
XS GIS Cut Line= 2
     1803018.723      242013.880     1803613.721      242391.352
#Sta/Elev= 30
       0 1419.32    15.0 1414.05    50.0 1406.33    55.0 1403.96    65.0 1390.10
    70.0 1384.50    75.0 1382.76   100.0 1382.87   119.9 1378.48   134.9 1377.52
   144.9 1378.80   159.9 1386.34   179.9 1380.88   189.9 1379.01   199.9 1378.01
   223.5 1377.71   234.9 1378.33   238.5 1379.47   289.8 1399.33   304.8 1402.54
   319.8 1403.99   339.8 1410.30   384.8 1429.72   434.8 1456.55   464.8 1471.60
   509.7 1491.88   539.7 1501.82   579.7 1510.22   609.7 1522.41   704.6 1549.13
#Mann= 3 , 0 , 0
       0     0.1       0   223.5   0.045       0   238.5     0.1       0
Bank Sta=   223.5,   238.5
Exp/Cntr=0.3,0.1

Type RM Length L Ch R = 1 ,846.8,426,431.9,436.5
XS GIS Cut Line= 3
     1802609.139      242180.509     1803151.806      242468.091
     1803445.041      242587.331
#Sta/Elev= 30
       0 1474.68    54.9 1455.04   104.9 1432.38   139.8 1413.75   159.8 1403.96
   184.8 1393.56   199.7 1388.84   249.7 1384.92   274.6 1378.73   304.6 1373.74
   384.5 1368.50   409.4 1367.81   437.4 1369.07   452.4 1371.66   479.3 1378.87
   509.3 1390.43   534.3 1392.82   539.3 1394.02   564.2 1405.10   604.2 1413.09
   614.2 1416.33   658.7 1433.64   683.4 1440.62   747.7 1468.00   772.4 1480.82
   792.2 1489.97   831.8 1505.93   891.1 1531.84   906.0 1539.00   930.7 1554.94
#Mann= 3 , 0 , 0
       0     0.1       0   437.4   0.045       0   452.4     0.1       0
Bank Sta=   437.4,   452.4
Exp/Cntr=0.3,0.1

Type RM Length L Ch R = 1 ,414.9,119.1,114.1,110.4
XS GIS Cut Line= 3
     1802453.914      242445.177     1802786.438      242753.517
     1803169.829      243014.169
#Sta/Elev= 30
       0 1435.93    39.9 1421.25    54.8 1414.06    69.8 1405.06    79.7 1400.57
   109.6 1390.64   144.5 1388.20   179.4 1384.51   209.3 1380.17   254.2 1370.86
   274.1 1368.27   378.7 1367.06   432.3 1363.60   443.5 1363.39   447.3 1363.45
   458.5 1364.02   478.4 1366.65   543.2 1369.24   548.2 1370.53   553.2 1372.73
   588.1 1389.56   623.0 1402.58   637.9 1404.90   677.8 1409.12   727.7 1428.74
   747.6 1434.33   767.5 1441.54   857.3 1470.88   872.2 1474.42   917.1 1479.54
#Mann= 3 , 0 , 0
       0     0.1       0   432.3   0.045       0   447.3     0.1       0
Bank Sta=   432.3,   447.3
Exp/Cntr=0.3,0.1

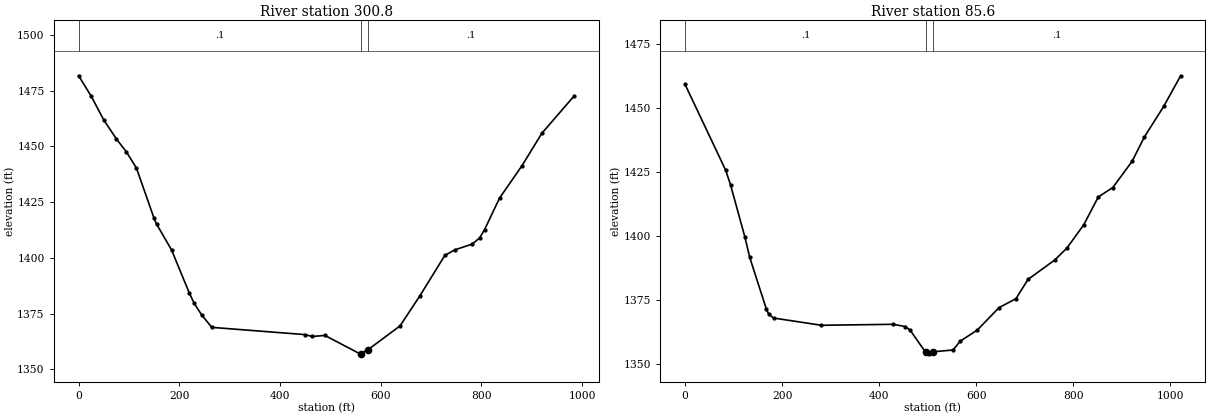
Type RM Length L Ch R = 1 ,300.8,208.7,215.2,221.7
XS GIS Cut Line= 3
     1802267.579      242554.272     1802783.103      242868.715
     1803136.683      243009.067
#Sta/Elev= 30
       0 1481.62    25.0 1472.46    49.9 1461.83    74.9 1453.34    94.8 1447.53
   114.8 1440.26   149.7 1417.81   154.7 1415.17   184.6 1403.54   219.6 1384.34
   229.6 1379.59   244.5 1374.35   264.5 1368.83   449.2 1365.59   464.1 1364.74
   489.1 1365.22   558.9 1356.96     560 1357.03     575 1358.85   638.4 1369.48
   678.0 1383.02   727.4 1401.09   747.1 1403.57   781.7 1406.15   796.5 1408.94
   806.4 1412.68   836.1 1426.80   880.5 1441.26   920.0 1455.81   984.3 1472.60
#Mann= 3 , 0 , 0
       0     0.1       0     560   0.045       0     575     0.1       0
Bank Sta=     560,     575
Exp/Cntr=0.3,0.1

Type RM Length L Ch R = 1 ,85.6,77.9,85.6,93.3
XS GIS Cut Line= 4
     1802224.393      242729.712     1802529.390      242911.900
     1802672.441      243068.447     1803125.887      243037.407
#Sta/Elev= 30
       0 1459.17    83.9 1425.56    93.8 1419.82   123.4 1399.43   133.2 1391.57
   167.8 1371.20   172.7 1369.24   182.6 1367.83   281.2 1365.00   429.2 1365.38
   453.9 1364.50   463.8 1363.15   496.1 1354.40   503.2 1353.83   511.1 1354.64
   552.5 1355.33   567.3 1358.79   602.3 1363.09   647.2 1371.89   682.2 1375.40
   707.2 1382.96   762.1 1390.51   787.1 1395.16   822.0 1404.29   852.0 1415.20
   882.0 1418.88   922.0 1429.20   946.9 1438.63   986.9 1450.61  1021.8 1462.58
#Mann= 3 , 0 , 0
       0     0.1       0   496.1   0.045       0   511.1     0.1       0
Bank Sta=   496.1,   511.1
Exp/Cntr=0.3,0.1